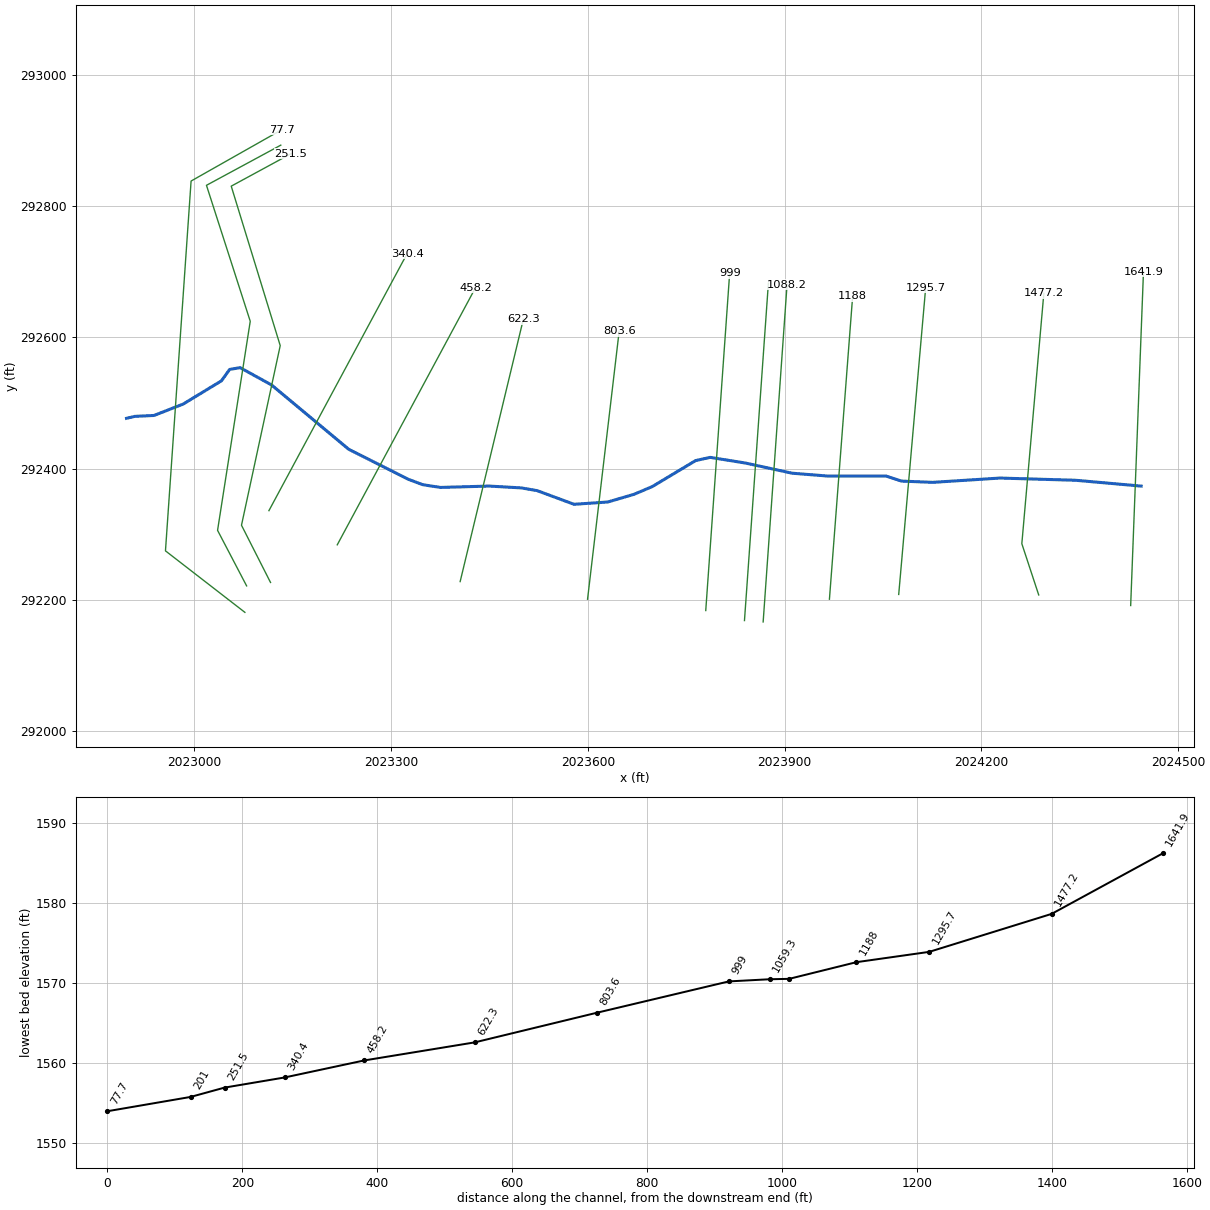
--- DNCNBR.prj (project) ---

Proj Title=DNCNBR
Current Plan=p01
Default Exp/Contr=0,0
English Units
Geom File=g01
Flow File=f01
Plan File=p01
BEGIN DESCRIPTION:
END DESCRIPTION:
DSS Export Rating Curves= 0
DSS Export Rating Curve Sorted= 0
DSS Export Volume Flow Curves= 0
DXF OffsetX= 0
DXF OffsetY= 0
DXF ScaleX= 0
DXF ScaleY= 0

--- DNCNBR.p01 (plan) ---

Plan Title=Floodplain
Program Version=4.00
Geom File=g01
Flow File=f01
K Sum by GR=0
Std Step Tol=0.01
Critical Tol=0.01
Num of Std Step Trials=20
Max Error Tol=0.3
Flow Tol Ratio=0.001
Split Flow NTrial=30
Split Flow Tol=0.02
Split Flow Ratio=0.02
Log Output Level=0
Friction Slope Method=1
Unsteady Friction Slope Method=2
Unsteady Bridges Friction Slope Method=1
Global Log Level=0
CheckData=False
Run HTab=0
Run UNet=0
Run PostProcess=0
UNET Theta=0
UNET Theta Warmup=0
UNET ZTol=0
UNET ZSATol=0
UNET MxIter=0
UNET MaxInSteps=0
UNET DtIC=0
UNET DtMin=0
UNET MaxCRTS=0
UNET WFStab=0
UNET SFStab=0
UNET WFX=0
UNET SFX=0
UNET DSS MLevel=0
UNET DZMax Abort=0
UNET Convert EG Bridges=0
UNET Use Existing IB Tables=0
UNET Froude Limit=0
UNET Froude Power=0
Write IC File=0
Echo Input=False
Echo Output=False
Write Detailed=0

--- DNCNBR.f01 (steady flow) ---

Flow Title=NFF Regression Equation
Program Version=4.00
Number of Profiles=1
Profile Names=P100yr
River Rch & RM=DNCNBR,Main      ,1641.9
555.4374
River Rch & RM=DNCNBR,Main      ,458.2
563.2220
River Rch & RM=DNCNBR,Main      ,251.5
566.1252
Boundary for River Rch & Prof#=DNCNBR,Main      ,1
Up Type=0
Dn Type=3
Dn Slope=0.015833

--- DNCNBR.g01 (geometry) ---

Geom Title=USGS 10m DEM
Program Version=4.10

River Reach=DNCNBR          ,Main
Reach XY= 30
     2024443.489      292373.279     2024343.648      292382.166
     2024228.223      292385.528     2024125.799      292378.966
     2024078.148      292380.913     2024054.703       292388.59
     2023965.719       292388.59     2023911.402      292392.927
     2023840.631      292408.363     2023786.648      292417.062
     2023764.425      292412.201     2023698.453      292372.618
     2023670.675      292360.812     2023630.398      292349.007
     2023579.009      292345.534     2023522.759      292366.368
     2023498.453      292370.534     2023449.445      292373.312
     2023375.536      292371.229     2023348.453      292375.395
     2023326.231      292383.729     2023235.487       292429.45
     2023117.898      292527.479     2023069.981      292553.868
     2023054.009       292551.09     2023041.509      292533.729
     2022983.175      292498.312     2022938.731      292480.951
     2022909.361      292479.562     2022896.834      292476.611

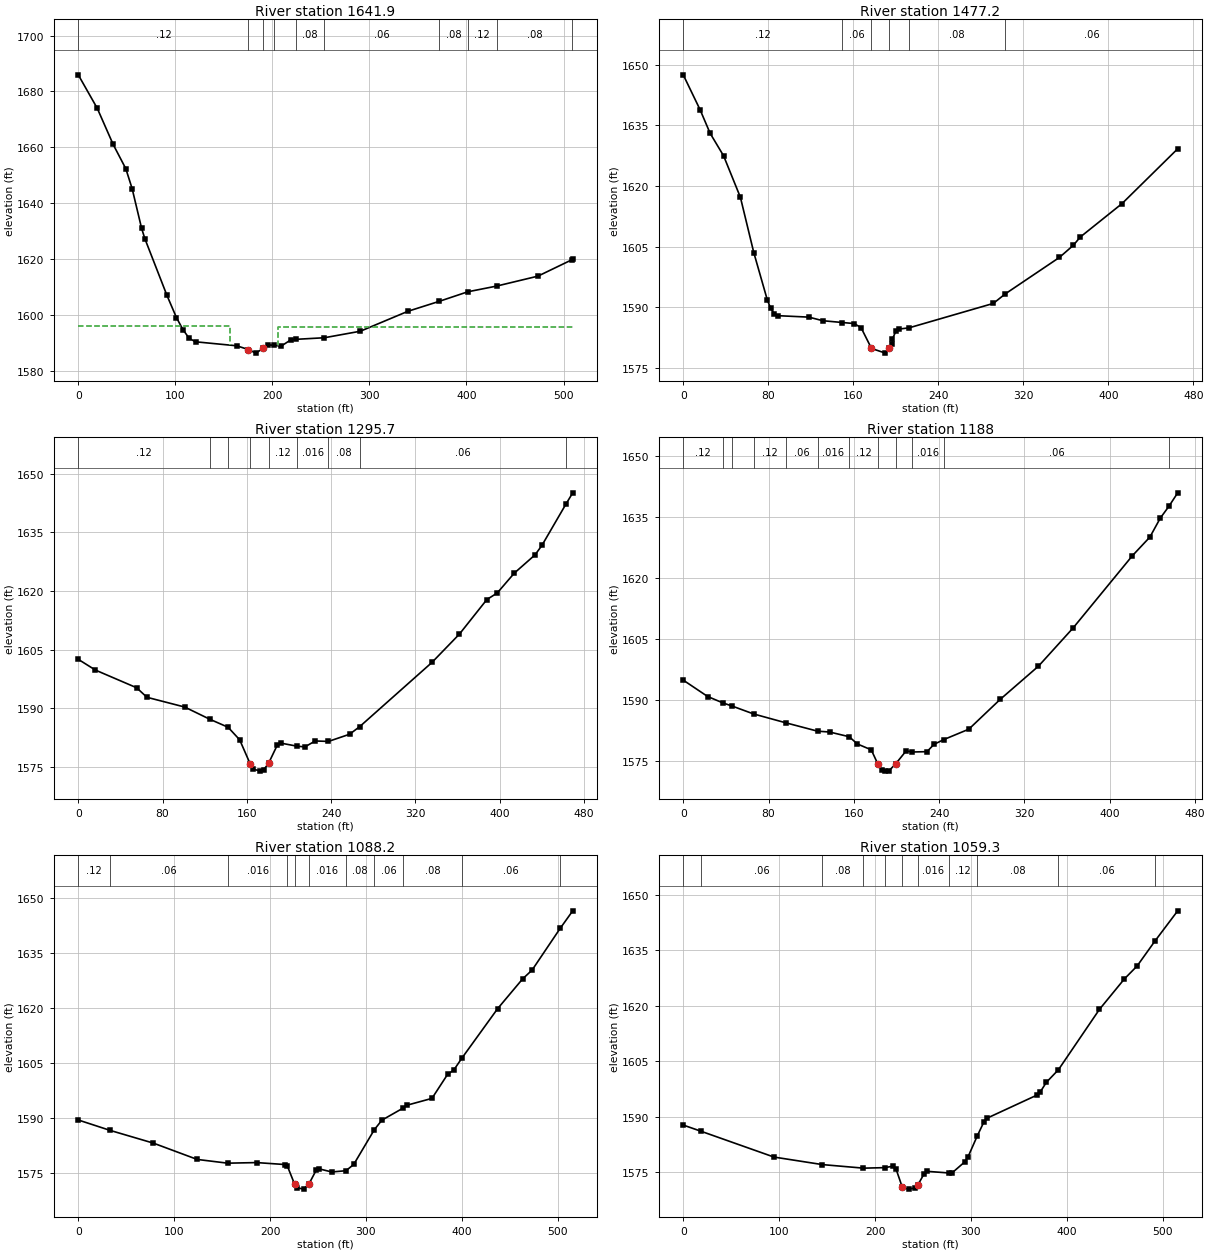
Type RM Length L Ch R = 1 ,1641.9  ,165.7,164.6,163.5
XS GIS Cut Line= 2
     2024427.559      292191.208      2024447.09      292700.323
#Sta/Elev= 30
       0 1685.92    19.6 1673.91    35.9 1661.03      49 1652.29    55.5 1645.17
    65.3 1630.89    68.6 1627.25    91.4  1606.9   101.2 1598.95   107.8  1594.7
   114.3 1591.53   120.8  1590.3   163.3 1588.87   175.4 1587.51   182.9 1586.24
   190.4  1587.9     196 1589.17  201.25 1589.07     209 1588.74   218.8 1590.95
  224.051591.176  253.611591.752   290.7 1594.09   339.7 1601.23  371.85 1604.78
   401.41608.213  430.961610.246   473.6 1613.81  509.071619.758   509.5 1619.86
#Mann= 10 ,-1 , 0
       0     .12       0   175.4    .045       0   190.4     .12       0
  201.25    .016       0  224.05     .08       0  253.61     .06       0
  371.85     .08       0   401.4     .12       0  430.96     .08       0
  509.07     .06       0
#XS Ineff= 2 , 0
          155.97 1596.05   205.4         1595.59
Permanent Ineff=
       F       F
Bank Sta=175.4,190.4
XS Rating Curve= 0 ,0
Exp/Cntr=0.3,0.1

Type RM Length L Ch R = 1 ,1477.2  ,181.5,181.5,181.4
XS GIS Cut Line= 3
     2024287.368      292207.354     2024261.648      292285.451
      2024295.18      292666.903
#Sta/Elev= 30
       0 1647.53    15.8 1638.92    25.3 1633.06      38 1627.47    53.8  1617.2
    66.4 1603.51    79.1 1591.82    82.2 1589.78    85.5 1588.43    88.8 1587.93
   118.2 1587.57   131.3 1586.68  149.661586.238   160.8 1585.98   167.3 1584.96
   177.1 1579.82   190.2 1578.66   193.5 1579.81  196.73 1581.01   196.8 1582.17
     200 1584.04   203.3 1584.62  212.361584.914   291.7 1590.96  302.981593.323
   353.9 1602.34     367 1605.34   373.5 1607.38   412.8 1615.66   465.2 1629.23
#Mann= 6 ,-1 , 0
       0     .12       0  149.66     .06       0   177.1    .045       0
   193.5    .016       0  212.36     .08       0  302.98     .06       0
Bank Sta=177.1,193.5
XS Rating Curve= 0 ,0
Exp/Cntr=0.3,0.1

Type RM Length L Ch R = 1 ,1295.7  ,107.3,107.8,107.8
XS GIS Cut Line= 2
     2024073.961      292208.071     2024115.059      292675.583
#Sta/Elev= 30
       0 1602.49    16.3 1599.74    55.4 1595.22    65.2 1592.78     101 1590.29
  125.021587.145  142.181585.123   153.2 1581.91     163 1575.85   166.2 1574.42
   172.7  1573.9     176 1574.25   180.6 1575.89     189 1580.62   192.3 1581.06
  207.811580.272   215.1  1580.1   224.9 1581.61  237.471581.499   257.5 1583.33
  267.121585.281   335.7  1601.7   361.8 1608.96   387.8 1617.78   397.6 1619.45
   413.9 1624.55   433.5  1629.2     440  1631.6     4631642.258   469.3 1645.07
#Mann= 9 ,-1 , 0
       0     .12       0  125.02    .016       0  142.18     .12       0
     163    .045       0   180.6     .12       0  207.81    .016       0
  237.47     .08       0  267.12     .06       0     463     .12       0
Bank Sta=163,180.6
XS Rating Curve= 0 ,0
Exp/Cntr=0.3,0.1

Type RM Length L Ch R = 1 ,1188    ,99.5,99.7,99.8
XS GIS Cut Line= 2
     2023968.357      292200.844     2024003.774       292663.17
#Sta/Elev= 30
       0 1594.94    22.9 1590.92   37.121589.358   45.681588.592   66.141586.626
   96.371584.454     1261582.412   137.2 1582.21  155.621581.055   163.3 1579.27
   176.3 1577.84  182.37 1574.43   186.1 1572.87   189.4 1572.61   192.7 1572.64
   199.2 1574.39     209 1577.57  214.871577.304   228.6 1577.39   235.1 1579.17
  244.491580.368   267.8  1582.9   297.2 1590.21   333.1 1598.36   365.7 1607.77
   421.2 1625.47   437.6 1630.04   447.4 1634.71   455.41637.573   463.7  1640.9
#Mann= 12 ,-1 , 0
       0     .12       0   37.12     .06       0   45.68     .08       0
   66.14     .12       0   96.37     .06       0     126    .016       0
  155.62     .12       0  182.37    .045       0   199.2     .06       0
  214.87    .016       0  244.49     .06       0   455.4     .12       0
Bank Sta=182.37,199.2
XS Rating Curve= 0 ,0
Exp/Cntr=0.3,0.1

Type RM Length L Ch R = 1 ,1088.2  ,28.8,28.9,28.8
XS GIS Cut Line= 2
     2023867.316      292166.208     2023903.774      292680.531
#Sta/Elev= 30
       0 1589.38    33.51586.518    78.3 1583.07     124 1578.62  155.68  1577.6
     186 1577.76   215.4 1577.23  218.171576.728   225.5 1571.92   228.4 1570.88
     235 1570.52   240.5 1571.91     248 1575.64   251.3 1576.04   264.3  1575.2
  279.111575.542   287.2 1577.24  308.721586.734   316.6 1589.33  338.331592.566
   342.6  1593.4   368.8 1595.27   385.1 1601.82   391.6 1603.02  400.071606.268
   437.3 1619.75   463.4 1627.88   473.2 1630.26  502.441641.618   515.6 1646.43
#Mann= 11 ,-1 , 0
       0     .12       0    33.5     .06       0  155.68    .016       0
  218.17     .12       0   225.5    .045       0   240.5    .016       0
  279.11     .08       0  308.72     .06       0  338.33     .08       0
  400.07     .06       0  502.44     .12       0
Bank Sta=225.5,240.5
XS Rating Curve= 0 ,0
Exp/Cntr=0.3,0.1

Type RM Length L Ch R = 1 ,1059.3  ,60.4,60.4,60.4
XS GIS Cut Line= 2
     2023838.844      292168.292     2023875.302      292682.614
#Sta/Elev= 30
       0 1587.77   18.481586.105    94.6 1579.13  145.081577.096  187.961576.134
  210.021576.271   218.6 1576.66   221.9 1575.89   228.4    1571     235 1570.47
   241.5 1570.77   244.6 1571.58   251.3 1574.67   254.5 1575.27  277.021574.833
   280.6 1574.92   293.7 1577.86     297 1579.21  306.631584.862   313.3  1588.5
   316.6 1589.61   368.8 1595.86     372  1596.6   378.6  1599.3  391.261602.727
     434 1619.02   460.1 1627.27   473.2 1630.71  491.991637.512   515.6 1645.63
#Mann= 11 ,-1 , 0
       0     .12       0   18.48     .06       0  145.08     .08       0
  187.96     .06       0  210.02    .016       0   228.4    .045       0
   244.6    .016       0  277.02     .12       0  306.63     .08       0
  391.26     .06       0  491.99     .12       0
Bank Sta=228.4,244.6
XS Rating Curve= 0 ,0
Exp/Cntr=0.3,0.1

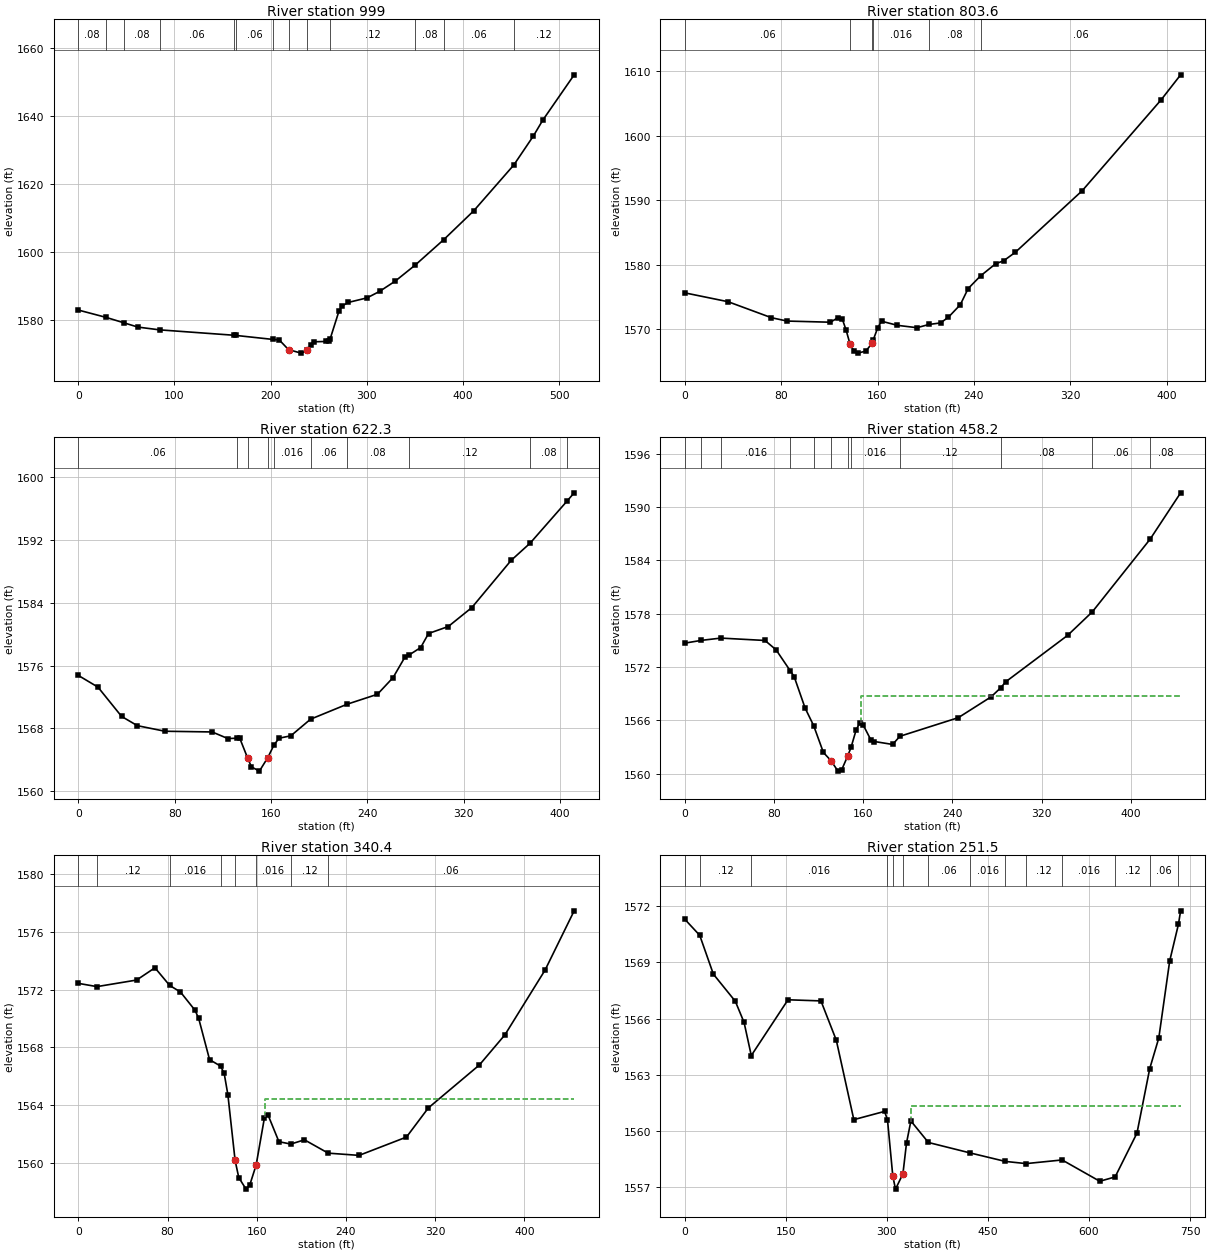
Type RM Length L Ch R = 1 ,999     ,195.6,195.3,193.6
XS GIS Cut Line= 2
     2023779.816      292183.569     2023816.274      292697.892
#Sta/Elev= 30
       0 1582.86   28.941580.699   47.591579.091      62 1577.85   84.631577.037
  162.071575.451  163.771575.407  202.481574.222   208.9 1574.09   218.6 1571.22
   231.7  1570.2   238.2 1571.06   241.5 1572.71   244.8 1573.53   257.8 1573.63
   261.1 1573.77   261.71574.239   270.9 1582.44   274.1 1584.03   280.6 1585.09
   300.2 1586.44   313.3 1588.35   329.6 1591.38  350.541596.134  380.151603.598
   411.2 1612.04  452.861625.503   473.2 1634.03     483 1638.69   515.6    1652
#Mann= 13 ,-1 , 0
       0     .08       0   28.94     .06       0   47.59     .08       0
   84.63     .06       0  162.07     .08       0  163.77     .06       0
  202.48     .12       0   218.6    .045       0   238.2    .016       0
   261.7     .12       0  350.54     .08       0  380.15     .06       0
  452.86     .12       0
Bank Sta=218.6,238.2
XS Rating Curve= 0 ,0
Exp/Cntr=0.3,0.1

Type RM Length L Ch R = 1 ,803.6   ,183.6,181.3,178.1
XS GIS Cut Line= 2
     2023599.627      292200.796     2023647.852      292609.572
#Sta/Elev= 30
       0 1575.62    35.9 1574.25    71.9 1571.77    84.9 1571.25   120.9 1571.07
   127.4  1571.8   130.7 1571.59   133.9 1569.85   137.2 1567.66   140.5  1566.6
   143.7 1566.28   150.3  1566.6  155.57 1567.83  156.281568.264   160.1 1570.17
   163.3 1571.23   176.4 1570.59   192.7 1570.22  202.781570.724   212.3 1570.96
   218.9 1571.86   228.7 1573.78   235.2 1576.28  245.511578.251   258.1 1580.14
   264.6 1580.58   274.4 1581.91   329.9 1591.45   395.3 1605.51   411.6 1609.41
#Mann= 6 ,-1 , 0
       0     .06       0   137.2    .045       0  155.57     .12       0
  156.28    .016       0  202.78     .08       0  245.51     .06       0
Bank Sta=137.2,155.57
XS Rating Curve= 0 ,0
Exp/Cntr=0.3,0.1

Type RM Length L Ch R = 1 ,622.3   ,169.6,164.2,158.1
XS GIS Cut Line= 2
     2023405.423      292227.667     2023501.778       292627.84
#Sta/Elev= 30
       0 1574.75    16.3 1573.26    35.9 1569.53      49 1568.35    71.9 1567.64
   111.1 1567.55   124.1 1566.71     1321566.754   133.9 1566.79   140.5 1564.24
   143.7  1563.1   150.3 1562.56   157.3 1564.29  162.381565.881   166.6 1566.75
   176.4 1567.06  192.761569.174  223.151571.085   248.3 1572.35   261.3 1574.48
   271.1 1577.08  274.591577.359   284.2  1578.3   290.7 1580.09   307.1 1580.98
   326.7  1583.4   359.3 1589.41  375.061591.601  405.441596.914   411.6 1598.01
#Mann= 10 ,-1 , 0
       0     .06       0     132     .08       0   140.5    .045       0
   157.3     .06       0  162.38    .016       0  192.76     .06       0
  223.15     .08       0  274.59     .12       0  375.06     .08       0
  405.44     .12       0
Bank Sta=140.5,157.3
XS Rating Curve= 0 ,0
Exp/Cntr=0.3,0.1

Type RM Length L Ch R = 1 ,458.2   ,117.7,117.7,117.8
XS GIS Cut Line= 2
     2023218.095      292283.758     2023428.689      292675.481
#Sta/Elev= 30
       0 1574.68   14.941574.993   32.331575.248    71.9 1574.98    81.8 1573.94
   94.711571.547    98.1 1570.91   107.9 1567.38  115.551565.411   124.3 1562.39
     131 1561.48   137.4 1560.29   140.6 1560.41     146 1561.96  149.091562.953
   153.7 1564.93     157 1565.72   160.2 1565.43   166.8 1563.82     170 1563.62
   186.4 1563.29  192.881564.206   245.3  1566.3   274.7 1568.64  283.231569.646
   287.8 1570.33   343.4 1575.56  365.541578.203  417.371586.375   444.7 1591.58
#Mann= 12 ,-1 , 0
       0     .06       0   14.94     .12       0   32.33    .016       0
   94.71     .08       0  115.55     .06       0     131    .045       0
     146     .06       0  149.09    .016       0  192.88     .12       0
  283.23     .08       0  365.54     .06       0  417.37     .08       0
#XS Ineff= 2 , 0
                          157.67         1568.74
Permanent Ineff=
       F       F
Bank Sta=131,146
XS Rating Curve= 0 ,0
Exp/Cntr=0.3,0.1

Type RM Length L Ch R = 1 ,340.4   ,81.5,89,95.2
XS GIS Cut Line= 2
     2023113.929      292335.842     2023324.522      292727.564
#Sta/Elev= 30
       0 1572.43   16.681572.204    52.3 1572.66    68.7 1573.51   81.941572.285
    91.6 1571.83   104.6 1570.57   107.9 1570.01   117.7 1567.14  127.551566.692
   130.8 1566.19   134.1 1564.72   140.6 1560.15   143.9 1558.96   150.4 1558.16
   153.7 1558.43   159.5 1559.84   166.8 1563.06     170 1563.33   179.9 1561.45
  190.561561.284   202.8 1561.58   224.11560.655   251.8  1560.5   294.3 1561.77
   313.9 1563.79   359.7 1566.77   382.6 1568.86   418.6 1573.35   444.7 1577.46
#Mann= 8 ,-1 , 0
       0     .08       0   16.68     .12       0   81.94    .016       0
  127.55     .12       0   140.6    .045       0   159.5    .016       0
  190.56     .12       0   224.1     .06       0
#XS Ineff= 2 , 0
                          167.61         1564.43
Permanent Ineff=
       F       F
Bank Sta=140.6,159.5
XS Rating Curve= 0 ,0
Exp/Cntr=0.3,0.1

Type RM Length L Ch R = 1 ,251.5   ,49.7,50.4,51.8
XS GIS Cut Line= 5
     2023116.361      292226.364      2023072.09      292313.604
      2023131.14      292587.421     2023056.465      292830.531
     2023147.611       292880.01
#Sta/Elev= 30
       0  1571.3   22.161570.442    42.4 1568.37      75 1566.92      88 1565.79
   98.691564.022   153.2    1567   202.1 1566.94   224.9 1564.84   250.9  1560.6
   296.5 1561.04  300.861560.595   308.8 1557.57   312.8 1556.89   323.8 1557.71
   329.1 1559.35   335.6 1560.53  361.571559.381  423.171558.826  475.74 1558.37
  506.641558.253   560.11558.448     616 1557.31  638.771557.542   671.2 1559.88
  690.121563.323   703.6 1564.96   719.8 1569.08  732.751571.031     736 1571.75
#Mann= 14 ,-1 , 0
       0     .08       0   22.16     .12       0   98.69    .016       0
  300.86     .08       0   308.8    .045       0   323.8    .016       0
  361.57     .06       0  423.17    .016       0  475.74     .08       0
  506.64     .12       0   560.1    .016       0  638.77     .12       0
  690.12     .06       0  732.75     .08       0
#XS Ineff= 2 , 0
                          335.23         1561.34
Permanent Ineff=
       F       F
Bank Sta=308.8,323.8
XS Rating Curve= 0 ,0
Exp/Cntr=0.3,0.1

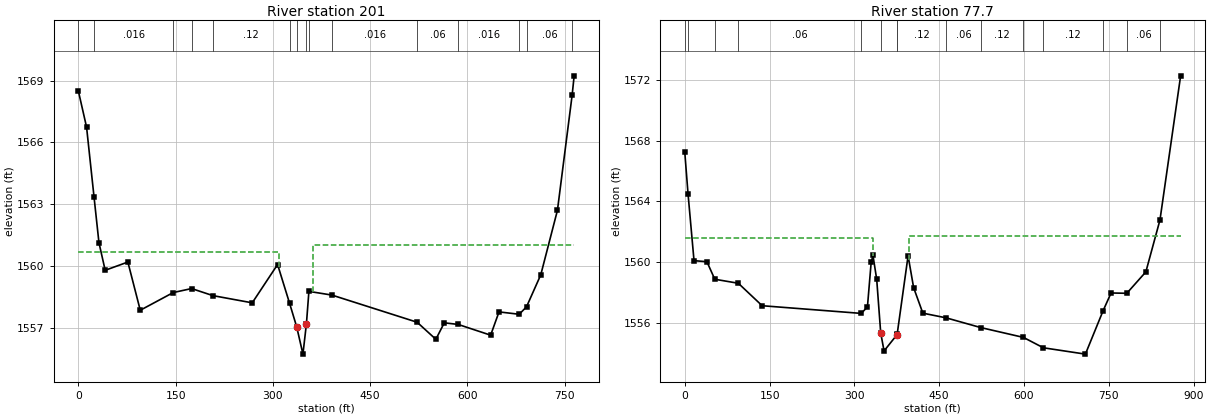
Type RM Length L Ch R = 1 ,201     ,120.6,123.3,125.4
XS GIS Cut Line= 5
     2023079.903      292221.156     2023035.632      292305.792
     2023085.445      292624.546     2023018.705      292831.833
     2023131.986      292893.031
#Sta/Elev= 30
       0  1568.5    12.7 1566.74   24.211563.351    31.8 1561.13    41.4 1559.79
    76.4 1560.19    95.5 1557.85  146.331558.709  174.681558.903  207.59 1558.56
   268.2 1558.21   307.3 1560.07   325.71558.199   336.8 1557.04   346.4 1555.72
   351.8  1557.2   355.61558.766  391.161558.586  522.531557.268   551.4 1556.44
   564.4 1557.24  585.721557.162   635.9 1556.64   648.8 1557.77  679.981557.655
  691.241558.018   713.2 1559.57   738.9  1562.7  761.551568.285   764.7 1569.23
#Mann= 15 ,-1 , 0
       0     .12       0   24.21    .016       0  146.33     .12       0
  174.68     .06       0  207.59     .12       0   325.7     .08       0
   336.8    .045       0   351.8     .08       0   355.6     .06       0
  391.16    .016       0  522.53     .06       0  585.72    .016       0
  679.98     .12       0  691.24     .06       0  761.55     .12       0
#XS Ineff= 2 , 0
          309.09 1560.69   362.5         1561.03
Permanent Ineff=
       F       F
Bank Sta=336.8,351.8
XS Rating Curve= 0 ,0
Exp/Cntr=0.3,0.1

Type RM Length L Ch R = 1 ,77.7    ,72.6,77.7,81.7
XS GIS Cut Line= 4
     2023077.298      292180.792     2022956.205      292274.542
     2022995.267      292838.344     2023133.288      292916.469
#Sta/Elev= 30
       0 1567.22    5.68 1564.51    16.3 1560.09    39.1 1560.02   53.031558.865
   94.66  1558.6   136.8 1557.12  312.021556.614     323 1557.04   329.6 1559.98
   332.8 1560.43   339.4 1558.86  346.47 1555.33   352.4 1554.14   375.3 1555.21
  375.651555.259   394.9 1560.41   404.7 1558.31     421 1556.63  462.27 1556.32
  523.351555.681  598.831555.033  634.161554.348   708.5 1553.93  739.89  1556.8
   753.9 1557.96   781.71557.939   815.4 1559.35  840.391562.776   876.9 1572.27
#Mann= 15 ,-1 , 0
       0     .12       0    5.68    .016       0   53.03     .12       0
   94.66     .06       0  312.02     .12       0  346.47    .045       0
   375.3     .08       0  375.65     .12       0  462.27     .06       0
  523.35     .12       0  598.83     .06       0  634.16     .12       0
  739.89    .016       0   781.7     .06       0  840.39     .12       0
#XS Ineff= 2 , 0
          332.39 1561.56  396.31         1561.72
Permanent Ineff=
       F       F
Bank Sta=346.47,375.3
XS Rating Curve= 0 ,0
Exp/Cntr=0.3,0.1

Chan Stop Cuts=-1
Use User Specified Reach Order=0
Composite Channel Slope=5